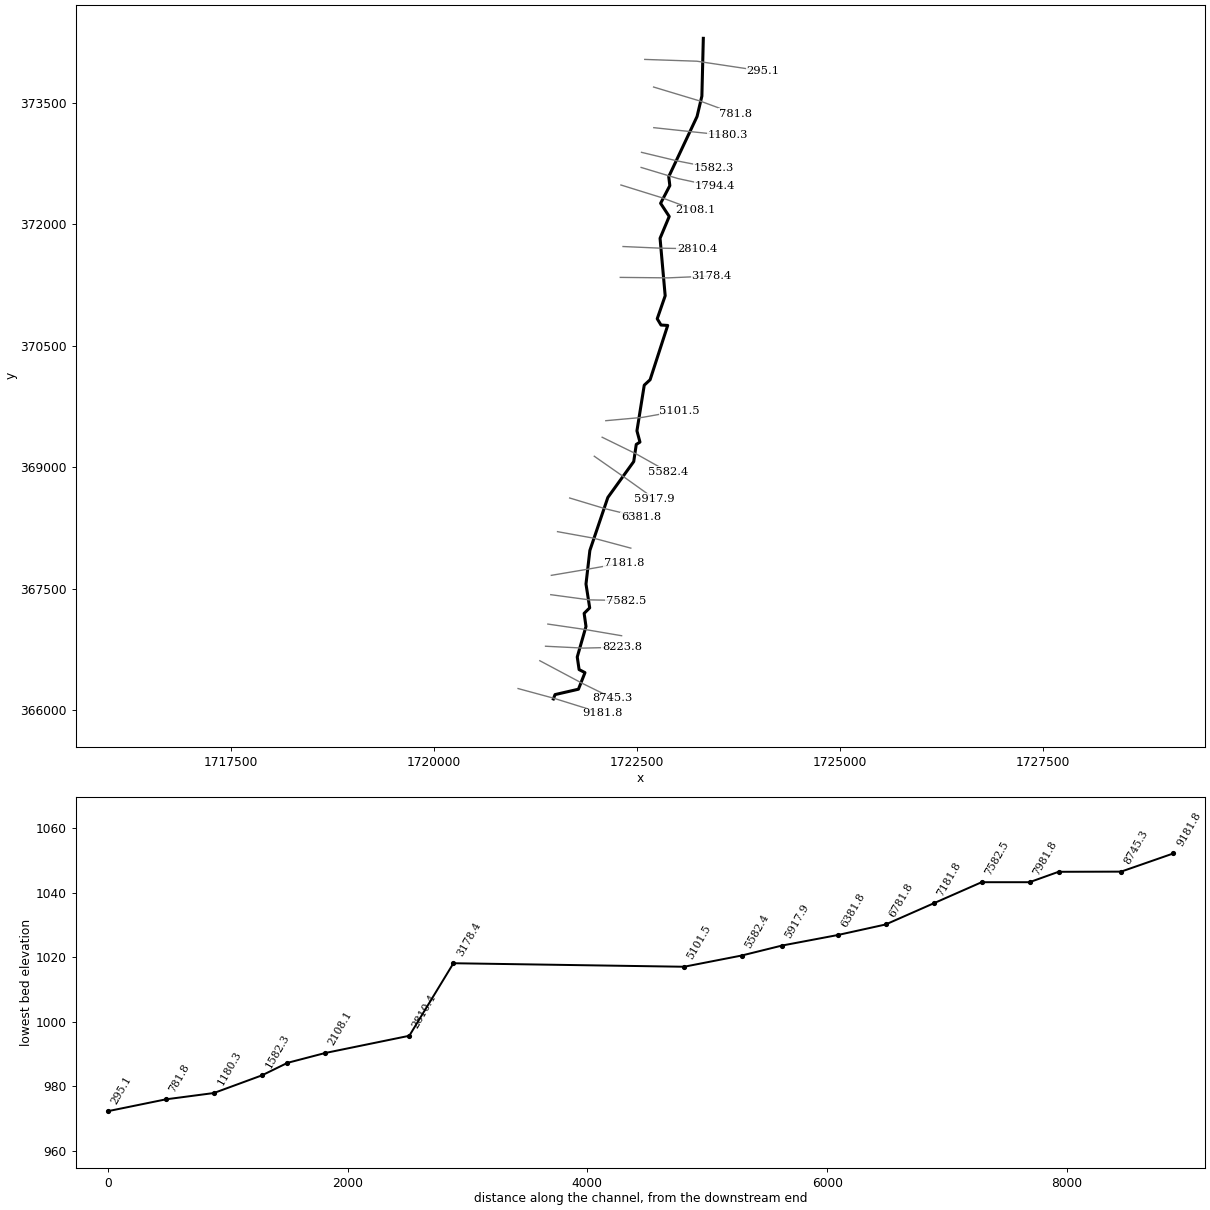
--- WhtstnRn.prj (project) ---

Proj Title=WhtstnRn
Current Plan=p01
Geom File=g01
Flow File=f01
Plan File=p01
DSS Export Rating Curves=0
DSS Export Rating Curve Sorted=0
DSS Export Volume Flow Curves=0
DXF OffsetX=0
DXF OffsetY=0
DXF ScaleX=0
DXF ScaleY=0

--- WhtstnRn.p01 (plan) ---

Plan Title=Floodplain
Program Version=4.00
Geom File=g01
Flow File=f01
K Sum by GR=0
Std Step Tol=0.01
Critical Tol=0.01
Num of Std Step Trials=20
Max Error Tol=0.3
Flow Tol Ratio=0.001
Split Flow NTrial=30
Split Flow Tol=0.02
Split Flow Ratio=0.02
Log Output Level=0
Friction Slope Method=1
Unsteady Friction Slope Method=2
Unsteady Bridges Friction Slope Method=1
Global Log Level=0
CheckData=False
Run HTab=0
Run UNet=0
Run PostProcess=0
UNET Theta=0
UNET Theta Warmup=0
UNET ZTol=0
UNET ZSATol=0
UNET MxIter=0
UNET MaxInSteps=0
UNET DtIC=0
UNET DtMin=0
UNET MaxCRTS=0
UNET WFStab=0
UNET SFStab=0
UNET WFX=0
UNET SFX=0
UNET DSS MLevel=0
UNET DZMax Abort=0
UNET Convert EG Bridges=0
UNET Use Existing IB Tables=0
UNET Froude Limit=0
UNET Froude Power=0
Write IC File=0
Echo Input=False
Echo Output=False
Write Detailed=0

--- WhtstnRn.f01 (steady flow) ---

Flow Title=NFF Regression Equation
Program Version=4.00
Number of Profiles=1
Profile Names=P100yr
River Rch & RM=WhtstnRn,Main      ,9181.8
759.9212
River Rch & RM=WhtstnRn,Main      ,6781.8
828.2421
River Rch & RM=WhtstnRn,Main      ,6381.8
918.6190
River Rch & RM=WhtstnRn,Main      ,5101.5
986.0567
River Rch & RM=WhtstnRn,Main      ,3178.4
1080.066
River Rch & RM=WhtstnRn,Main      ,2108.1
1089.806
River Rch & RM=WhtstnRn,Main      ,2108.1
1302.469
River Rch & RM=WhtstnRn,Main      ,295.1
1330.911
Boundary for River Rch & Prof#=WhtstnRn,Main      ,1
Up Type=0
Dn Type=3
Dn Slope=0.014179

--- WhtstnRn.g01 (geometry) ---

Geom Title=USGS 3m DEM
Program Version=4.00

River Reach=WhtstnRn     ,Main
Reach XY= 30
     1721468.883      366139.957     1721489.589      366193.793
     1721777.407      366260.053     1721858.162      366465.046
     1721785.689      366502.317     1721762.912      366657.615
     1721870.585      367034.470     1721847.808      367195.979
     1721916.139      367264.310     1721870.585      367558.339
     1721918.210      367972.466     1722139.768      368626.785
     1722458.645      369069.901     1722489.704      369281.105
     1722535.258      369310.094     1722497.987      369448.826
     1722588.162      370012.479     1722660.331      370079.493
     1722876.839      370749.637     1722794.360      370754.792
     1722747.966      370832.117     1722845.910      371115.639
     1722782.854      371824.992     1722895.756      372094.526
     1722789.550      372257.066     1722903.278      372475.361
     1722889.734      372585.711     1723238.422      373328.212
     1723297.892      373579.947     1723315.647      374293.038

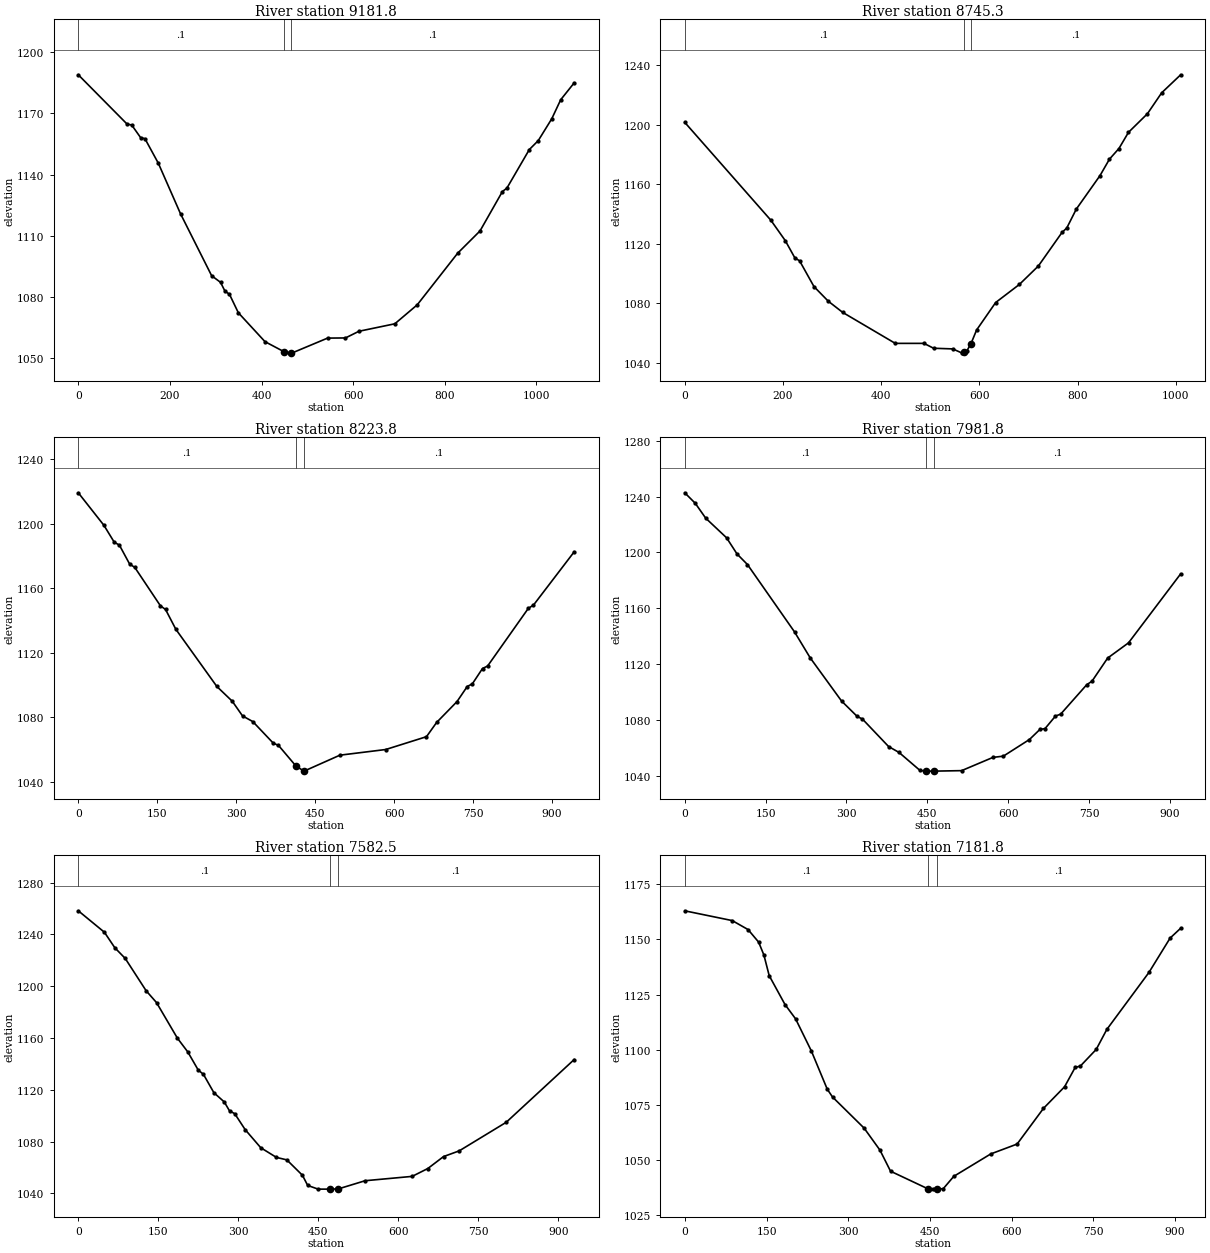
Type RM Length L Ch R = 1 ,9181.8,442.924,436.514,427.912
XS GIS Cut Line= 3
     1721034.028      366268.310     1721473.921      366148.594
     1722071.762      365961.931
#Sta/Elev= 30
       0 1188.97   106.7 1164.70   116.4 1164.35   135.8 1158.16   145.5 1157.56
   174.6 1145.54   223.1 1120.68   291.0 1090.27   310.4 1087.02   320.1 1082.67
   329.8 1081.19   349.2 1072.09   407.4 1057.89   448.4 1053.01   463.4 1052.32
   465.7 1052.25   544.0 1059.63   583.1 1059.71   612.5 1062.99   690.8 1066.66
   739.7 1075.98   827.8 1101.30   876.7 1112.27   925.6 1131.63   935.4 1133.31
   984.3 1152.25  1003.9 1156.67  1033.3 1167.37  1052.8 1176.72  1082.2 1185.01
#Mann= 3 , 0 , 0
       0     0.1       0   448.4   0.045       0   463.4     0.1       0
Bank Sta=   448.4,   463.4
Exp/Cntr=0.3,0.1

Type RM Length L Ch R = 1 ,8745.3,511.574,521.419,534.847
XS GIS Cut Line= 3
     1721301.696      366611.916     1721834.566      366327.609
     1722198.642      366148.464
#Sta/Elev= 30
       0 1201.70   175.3 1135.92   204.6 1122.23   224.1 1110.63   233.8 1108.63
   263.0 1091.35   292.2 1081.49   321.5 1073.98   428.6 1053.15   487.1 1053.15
   506.6 1049.87   545.5 1049.43   565.0 1046.59   567.9 1047.09   574.7 1048.27
   582.9 1053.04   594.2 1062.12   633.0 1080.60   681.3 1092.76   719.9 1105.12
   768.2 1127.74   777.9 1130.73   797.2 1143.39   845.5 1165.93   864.8 1177.01
   884.1 1184.16   903.5 1195.02   942.1 1207.53   971.1 1221.60  1009.7 1233.69
#Mann= 3 , 0 , 0
       0     0.1       0   567.9   0.045       0   582.9     0.1       0
Bank Sta=   567.9,   582.9
Exp/Cntr=0.3,0.1

Type RM Length L Ch R = 1 ,8223.8,244.096,242.067,239.422
XS GIS Cut Line= 3
     1721372.263      366790.530     1721839.507      366767.411
     1722313.390      366779.284
#Sta/Elev= 30
       0 1219.19    48.7 1198.99    68.2 1188.56    78.0 1186.74    97.5 1174.97
   107.2 1172.95   155.9 1149.11   165.7 1146.81   185.2 1134.54   263.1 1099.06
   292.4 1089.90   311.9 1080.79   331.4 1077.28   370.4 1063.85   380.1 1062.53
   413.2 1049.76   428.2 1046.61   428.8 1046.54   496.8 1056.43   583.9 1059.95
   661.3 1067.91   680.6 1076.75   719.3 1089.69   738.7 1099.04   748.4 1100.68
   767.7 1110.20   777.4 1111.74   854.8 1147.55   864.5 1149.53   941.8 1182.57
#Mann= 3 , 0 , 0
       0     0.1       0   413.2   0.045       0   428.2     0.1       0
Bank Sta=   413.2,   428.2
Exp/Cntr=0.3,0.1

Type RM Length L Ch R = 1 ,7981.8,399.296,399.247,401.972
XS GIS Cut Line= 3
     1721400.855      367064.087     1721851.705      366998.425
     1722309.346      366920.243
#Sta/Elev= 30
       0 1242.76    19.4 1235.28    38.8 1224.60    77.5 1210.54    96.9 1198.95
   116.3 1191.34   203.6 1143.08   232.6 1124.52   290.8 1093.57   319.9 1082.48
   329.6 1080.63   378.1 1060.93   397.4 1056.72   436.2 1043.86   445.9 1043.31
   448.1 1043.31   463.1 1043.31   513.6 1043.66   571.7 1053.15   591.0 1054.04
   639.4 1065.96   658.7 1073.15   668.4 1073.82   687.7 1082.76   697.4 1084.18
   745.8 1105.28   755.4 1107.72   784.5 1124.33   823.2 1135.24   919.9 1184.65
#Mann= 3 , 0 , 0
       0     0.1       0   448.1   0.045       0   463.1     0.1       0
Bank Sta=   448.1,   463.1
Exp/Cntr=0.3,0.1

Type RM Length L Ch R = 1 ,7582.5,393.881,400.698,405.176
XS GIS Cut Line= 3
     1721436.700      367426.870     1721911.394      367362.883
     1722362.078      367354.234
#Sta/Elev= 30
       0 1258.25    48.9 1241.71    68.4 1229.74    88.0 1221.45   127.1 1196.55
   146.6 1187.40   185.7 1159.94   205.3 1149.26   224.8 1135.29   234.6 1131.98
   254.2 1117.78   273.7 1110.63   283.5 1103.76   293.3 1101.58   312.8 1089.30
   342.1 1075.28   371.5 1067.81   391.0 1065.90   420.3 1053.99   430.1 1046.16
   449.7 1043.31   472.6 1043.31   487.6 1043.49   537.8 1049.80   626.0 1053.15
   655.4 1059.23   684.8 1068.44   714.2 1072.85   802.4 1094.93   929.8 1143.38
#Mann= 3 , 0 , 0
       0     0.1       0   472.6   0.045       0   487.6     0.1       0
Bank Sta=   472.6,   487.6
Exp/Cntr=0.3,0.1

Type RM Length L Ch R = 1 ,7181.8,407.778,400.055,389.933
XS GIS Cut Line= 3
     1721443.799      367665.502     1721892.431      367741.465
     1722340.410      367821.072
#Sta/Elev= 30
       0 1163.00    87.1 1158.57   116.2 1154.48   135.5 1148.81   145.2 1142.93
   154.9 1133.59   183.9 1120.49   203.3 1114.01   232.3 1099.41   261.4 1082.10
   271.1 1078.54   329.2 1064.39   358.2 1054.42   377.6 1044.87     447 1036.79
   455.0 1036.74     462 1036.74   474.4 1036.95   493.7 1042.54   561.5 1052.70
   609.9 1057.19   658.3 1073.38   697.0 1083.17   716.4 1091.93   726.1 1092.60
   755.1 1100.13   774.5 1109.17   851.9 1135.06   890.7 1150.63   910.0 1155.08
#Mann= 3 , 0 , 0
       0     0.1       0     447   0.045       0     462     0.1       0
Bank Sta=     447,     462
Exp/Cntr=0.3,0.1

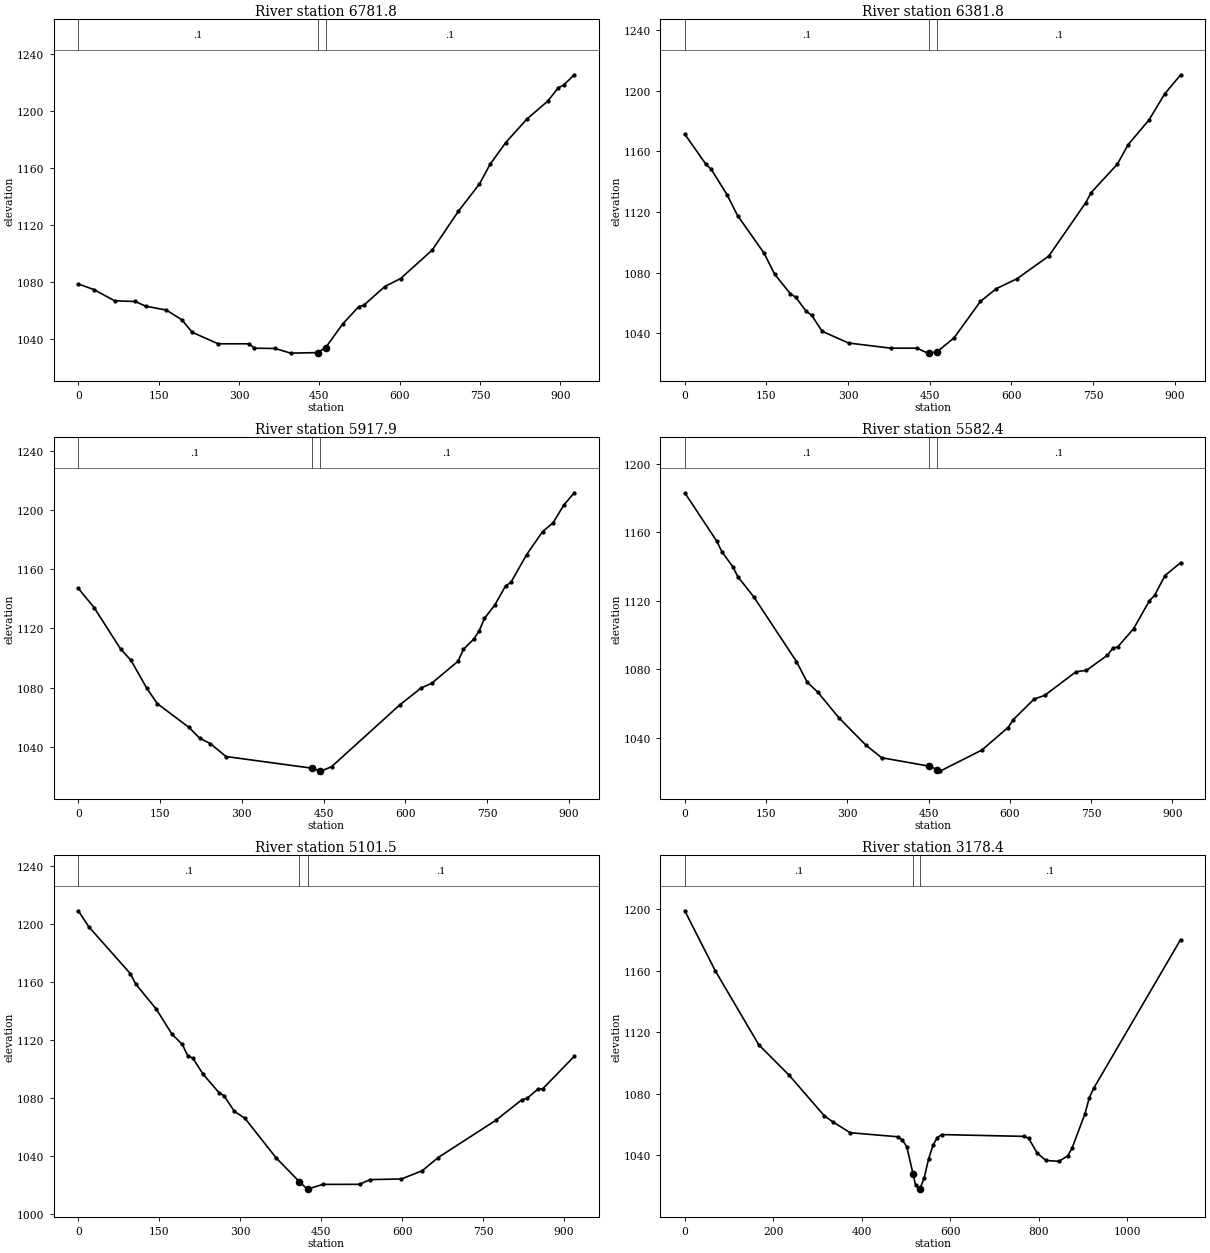
Type RM Length L Ch R = 1 ,6781.8,402.859,400,400.588
XS GIS Cut Line= 3
     1721520.151      368204.574     1721967.317      368123.605
     1722422.618      368001.283
#Sta/Elev= 30
       0 1078.71    29.0 1074.81    67.7 1066.93   106.4 1066.43   125.7 1063.16
   164.4 1060.40   193.4 1053.57   212.7 1044.79   261.1 1036.74   319.1 1036.74
   328.7 1033.62   367.4 1033.46   396.4 1030.18   446.9 1030.55   461.9 1034.04
   493.7 1050.70   523.2 1062.65   533.0 1063.74   572.3 1076.95   601.8 1082.56
   660.7 1102.49   709.8 1129.85   749.1 1148.99   768.7 1162.62   798.2 1178.06
   837.5 1194.47   876.8 1207.21   896.4 1216.56   906.2 1218.34   925.9 1225.58
#Mann= 3 , 0 , 0
       0     0.1       0   446.9   0.045       0   461.9     0.1       0
Bank Sta=   446.9,   461.9
Exp/Cntr=0.3,0.1

Type RM Length L Ch R = 1 ,6381.8,471.178,463.873,455.283
XS GIS Cut Line= 3
     1721669.684      368620.107     1722105.967      368488.024
     1722547.896      368380.374
#Sta/Elev= 30
       0 1171.28    38.8 1151.43    48.5 1148.14    77.6 1131.32    97.0 1117.57
   145.5 1092.88   164.9 1079.03   194.0 1065.98   203.7 1063.81   223.1 1054.44
   232.8 1052.00   252.2 1041.31   300.7 1033.57   378.2 1030.18   426.7 1030.18
   446.1 1026.90   448.3 1026.90   463.3 1027.78   494.5 1036.93   542.9 1060.98
   572.0 1069.36   610.7 1076.07   668.7 1090.96   736.5 1126.15   746.2 1132.72
   794.6 1151.54   813.9 1164.20   852.6 1180.63   881.7 1198.00   910.7 1210.41
#Mann= 3 , 0 , 0
       0     0.1       0   448.3   0.045       0   463.3     0.1       0
Bank Sta=   448.3,   463.3
Exp/Cntr=0.3,0.1

Type RM Length L Ch R = 1 ,5917.9,330.515,335.487,338.989
XS GIS Cut Line= 3
     1721972.647      369135.298     1722345.393      368874.376
     1722715.227      368609.275
#Sta/Elev= 30
       0 1146.99    29.0 1134.01    77.4 1106.19    96.8 1098.34   125.8 1079.46
   145.2 1069.12   203.3 1053.10   222.7 1045.86   242.0 1042.28   271.1 1033.49
   428.9 1025.62   443.9 1023.79   445.3 1023.64   464.7 1026.60   590.5 1068.53
   629.3 1079.79   648.6 1082.96   697.0 1097.87   706.7 1105.79   726.1 1112.89
   735.8 1118.44   745.4 1126.72   764.8 1136.02   784.2 1148.76   793.8 1150.99
   822.9 1169.84   851.9 1185.25   871.3 1191.24   890.7 1203.05   910.0 1211.50
#Mann= 3 , 0 , 0
       0     0.1       0   428.9   0.045       0   443.9     0.1       0
Bank Sta=   428.9,   443.9
Exp/Cntr=0.3,0.1

Type RM Length L Ch R = 1 ,5582.4,468.017,480.951,493.734
XS GIS Cut Line= 3
     1722069.651      369369.852     1722484.103      369166.614
     1722879.664      368944.133
#Sta/Elev= 30
       0 1183.06    58.9 1154.88    68.7 1148.58    88.4 1139.96    98.2 1133.96
   127.7 1122.16   206.2 1084.54   225.9 1072.49   245.5 1066.68   284.8 1051.60
   333.9 1035.86   363.4 1028.38   451.2 1023.45   466.2 1021.46   471.3 1020.55
   548.5 1032.86   596.8 1046.02   606.4 1050.58   645.1 1062.68   664.4 1064.76
   722.3 1078.60   741.6 1079.39   780.3 1088.26   789.9 1092.18   799.6 1093.20
   828.5 1103.68   857.5 1119.90   867.2 1123.15   886.5 1134.73   915.4 1142.27
#Mann= 3 , 0 , 0
       0     0.1       0   451.2   0.045       0   466.2     0.1       0
Bank Sta=   451.2,   466.2
Exp/Cntr=0.3,0.1

Type RM Length L Ch R = 1 ,5101.5,1921.176,1923.103,1919.304
XS GIS Cut Line= 3
     1722114.459      369574.045     1722565.762      369614.948
     1723023.962      369696.860
#Sta/Elev= 30
       0 1209.10    19.3 1198.13    96.4 1165.74   106.1 1158.73   144.6 1141.16
   173.5 1123.99   192.8 1116.86   202.5 1109.19   212.1 1107.37   231.4 1096.29
   260.3 1083.71   270.0 1081.43   289.2 1070.73   308.5 1065.99   366.4 1038.66
   409.7 1022.11   424.2 1017.06   424.7 1017.06   453.2 1020.34   521.0 1020.37
   540.4 1023.62   598.6 1024.08   637.4 1029.81   666.5 1038.83   773.2 1064.48
   821.6 1078.69   831.3 1079.73   850.7 1085.83   860.4 1086.32   918.6 1108.64
#Mann= 3 , 0 , 0
       0     0.1       0   409.7   0.045       0   424.7     0.1       0
Bank Sta=   409.7,   424.7
Exp/Cntr=0.3,0.1

Type RM Length L Ch R = 1 ,3178.4,368.762,367.982,367.778
XS GIS Cut Line= 3
     1722292.746      371342.677     1722883.000      371336.800
     1723412.784      371359.863
#Sta/Elev= 30
       0 1198.79    68.9 1159.85   167.2 1111.84   236.1 1091.99   314.8 1065.88
   334.5 1061.82   373.8 1054.76   482.1 1052.13   491.9 1049.97   501.7 1045.67
     516 1027.80   521.4 1020.93     531 1018.23   531.3 1018.15   541.1 1025.58
   550.9 1037.62   560.8 1046.53   570.6 1051.57   580.4 1053.55   767.0 1052.39
   776.9 1051.20   796.5 1041.53   816.1 1036.75   845.6 1036.19   865.2 1039.73
   875.1 1044.65   904.5 1067.13   914.3 1077.54   924.2 1083.63  1120.6 1180.15
#Mann= 3 , 0 , 0
       0     0.1       0     516   0.045       0     531     0.1       0
Bank Sta=     516,     531
Exp/Cntr=0.3,0.1

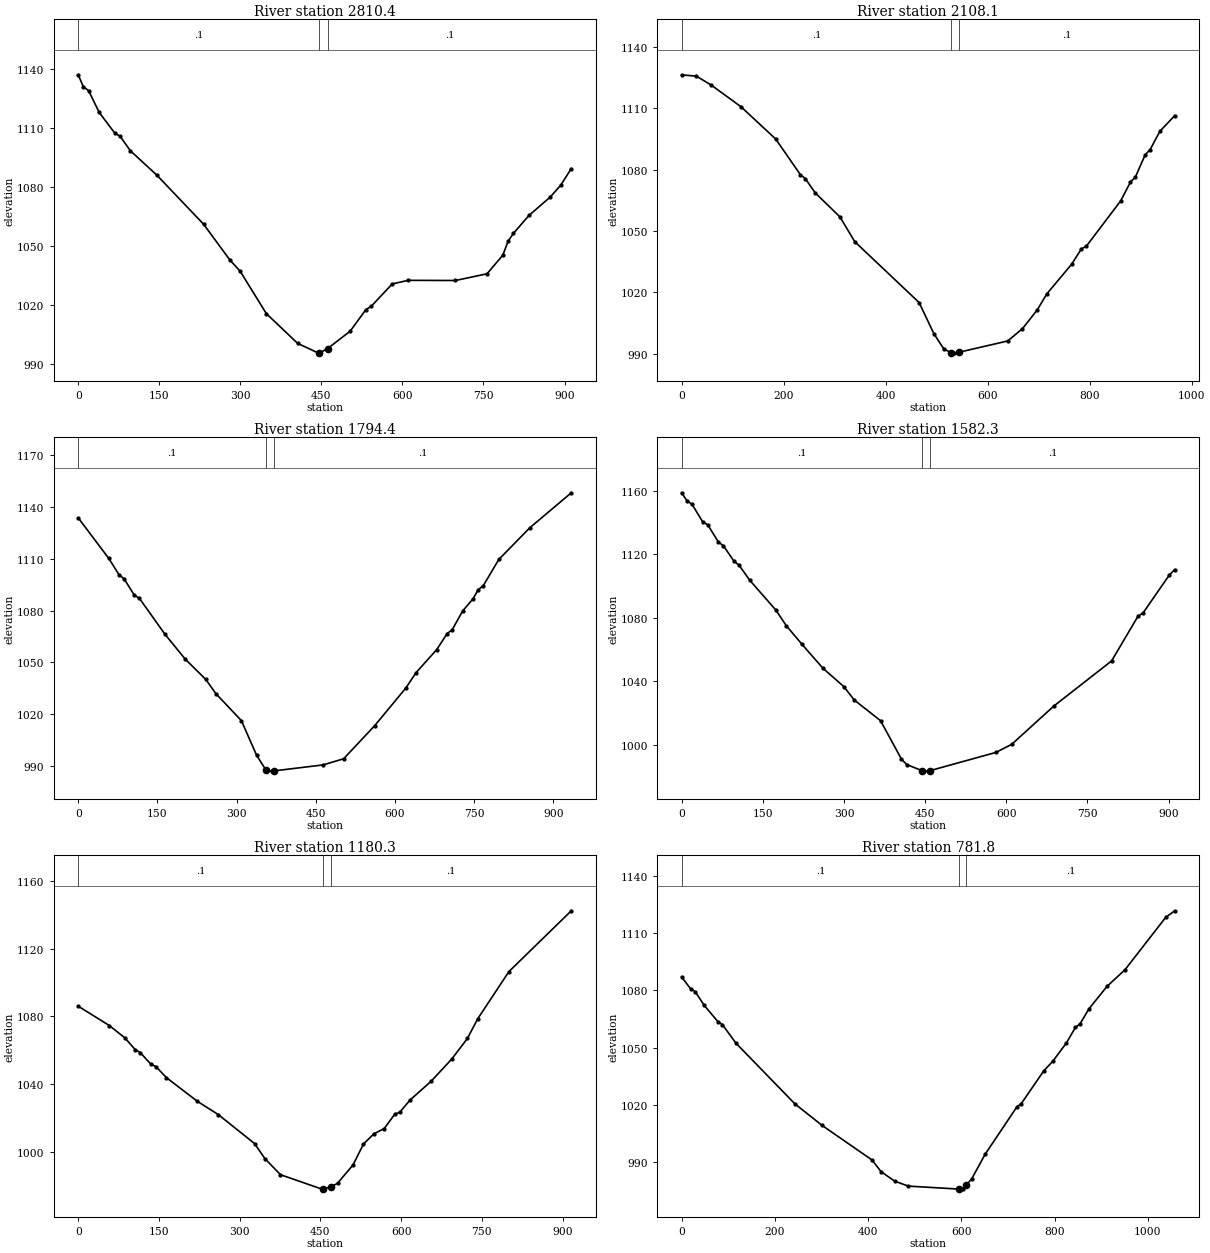
Type RM Length L Ch R = 1 ,2810.4,708.754,702.288,694.618
XS GIS Cut Line= 3
     1722326.742      371723.652     1722780.774      371703.539
     1723238.655      371695.043
#Sta/Elev= 30
       0 1137.06     9.7 1130.94    19.3 1129.03    38.7 1118.02    67.7 1107.43
    77.4 1105.88    96.7 1098.42   145.0 1086.23   232.1 1061.13   280.4 1043.08
   299.8 1037.21   348.1 1015.74   406.1 1000.58   444.8  995.63   446.5  995.68
   461.5  997.96   503.2 1006.75   532.4 1017.77   542.2 1019.41   581.1 1030.78
   610.4 1032.62   698.1 1032.54   756.5 1035.94   785.8 1045.41   795.5 1052.47
   805.3 1056.45   834.5 1065.69   873.5 1074.94   892.9 1080.96   912.4 1089.41
#Mann= 3 , 0 , 0
       0     0.1       0   446.5   0.045       0   461.5     0.1       0
Bank Sta=   446.5,   461.5
Exp/Cntr=0.3,0.1

Type RM Length L Ch R = 1 ,2108.1,309.311,313.722,315.392
XS GIS Cut Line= 3
     1722300.719      372483.050     1722800.827      372327.247
     1723216.020      372173.180
#Sta/Elev= 30
       0 1126.33    29.1 1125.66    58.2 1121.30   116.4 1110.73   184.3 1094.98
   232.8 1077.56   242.5 1075.60   261.9 1068.64   310.4 1056.87   339.5 1044.75
   465.6 1015.00   494.7  999.74   514.1  992.30   528.3  990.48   533.4  990.27
   543.3  990.67   639.3  996.21   668.2 1002.20   697.1 1011.35   716.4 1019.35
   764.5 1033.65   783.8 1041.23   793.4 1042.51   860.8 1064.68   880.0 1073.88
   889.7 1076.37   908.9 1087.24   918.5 1089.73   937.8 1098.77   966.7 1106.35
#Mann= 3 , 0 , 0
       0     0.1       0   528.3   0.045       0   543.3     0.1       0
Bank Sta=   528.3,   543.3
Exp/Cntr=0.3,0.1

Type RM Length L Ch R = 1 ,1794.4,211.071,212.081,214.017
XS GIS Cut Line= 3
     1722549.597      372699.706     1723002.684      372562.678
     1723452.935      372465.550
#Sta/Elev= 30
       0 1133.62    58.0 1110.12    77.3 1100.76    86.9 1098.38   106.3 1088.90
   115.9 1087.12   164.2 1066.38   202.9 1051.90   241.5 1040.27   260.8 1032.03
   309.1 1016.42   338.1  996.28   355.5  987.96   367.1  987.22   370.5  987.35
   463.7  990.80   502.8  994.35   561.6 1013.47   620.4 1035.15   640.0 1044.12
   679.2 1057.50   698.8 1066.64   708.6 1068.98   728.2 1079.74   747.8 1086.77
   757.6 1091.99   767.4 1094.44   796.8 1109.56   855.6 1127.89   934.0 1148.06
#Mann= 3 , 0 , 0
       0     0.1       0   355.5   0.045       0   370.5     0.1       0
Bank Sta=   355.5,   370.5
Exp/Cntr=0.3,0.1

Type RM Length L Ch R = 1 ,1582.3,398.981,401.942,403.893
XS GIS Cut Line= 3
     1722554.522      372885.982     1722996.552      372779.673
     1723444.497      372691.621
#Sta/Elev= 30
       0 1158.71     9.7 1153.82    19.3 1151.46    38.7 1140.57    48.4 1138.53
    67.7 1127.84    77.4 1125.30    96.7 1115.66   106.4 1113.01   125.7 1103.71
   174.1 1084.86   193.5 1074.97   222.5 1063.24   261.2 1048.15   299.9 1036.57
   319.2 1028.11   367.6 1015.15   406.3  990.91   415.9  987.49   444.6  983.62
   454.6  983.35   459.6  983.71   580.9  995.14   610.0 1000.22   687.7 1024.30
   794.6 1052.78   843.2 1080.82   852.9 1083.07   901.4 1106.95   911.2 1110.27
#Mann= 3 , 0 , 0
       0     0.1       0   444.6   0.045       0   459.6     0.1       0
Bank Sta=   444.6,   459.6
Exp/Cntr=0.3,0.1

Type RM Length L Ch R = 1 ,1180.3,403.114,398.571,392.724
XS GIS Cut Line= 3
     1722705.634      373190.611     1723165.463      373141.086
     1723616.544      373094.404
#Sta/Elev= 30
       0 1085.95    57.8 1074.53    86.7 1067.21   106.0 1060.25   115.6 1058.44
   134.9 1051.70   144.5 1050.25   163.8 1043.76   221.6 1029.69   260.1 1021.94
   327.6 1004.80   346.9  995.85   375.8  986.38   452.9  977.85   454.8  977.86
   469.8  979.25   481.8  981.30   510.7  992.21   530.0 1004.48   549.3 1010.52
   568.6 1013.66   587.9 1022.04   597.6 1023.36   616.9 1030.61   655.5 1041.53
   694.1 1054.74   723.0 1066.86   742.3 1078.52   800.2 1106.39   916.0 1142.29
#Mann= 3 , 0 , 0
       0     0.1       0   454.8   0.045       0   469.8     0.1       0
Bank Sta=   454.8,   469.8
Exp/Cntr=0.3,0.1

Type RM Length L Ch R = 1 ,781.8,483.416,486.695,491.361
XS GIS Cut Line= 3
     1722703.205      373691.971     1723280.356      373517.680
     1723706.917      373359.871
#Sta/Elev= 30
       0 1087.06    19.4 1080.83    29.2 1079.37    48.6 1072.17    77.8 1063.67
    87.5 1062.12   116.7 1052.35   243.1 1020.55   301.4 1009.28   408.4  991.18
   427.9  985.05   457.0  980.11   486.2  977.48   595.4  975.92   602.9  975.90
   610.4  978.00   622.2  981.23   651.3  994.24   719.0 1018.94   728.7 1020.74
   777.1 1037.94   796.4 1042.94   825.5 1052.50   844.8 1060.66   854.5 1062.43
   873.8 1070.35   912.6 1082.16   951.3 1090.90  1038.4 1118.28  1057.7 1121.73
#Mann= 3 , 0 , 0
       0     0.1       0   595.4   0.045       0   610.4     0.1       0
Bank Sta=   595.4,   610.4
Exp/Cntr=0.3,0.1

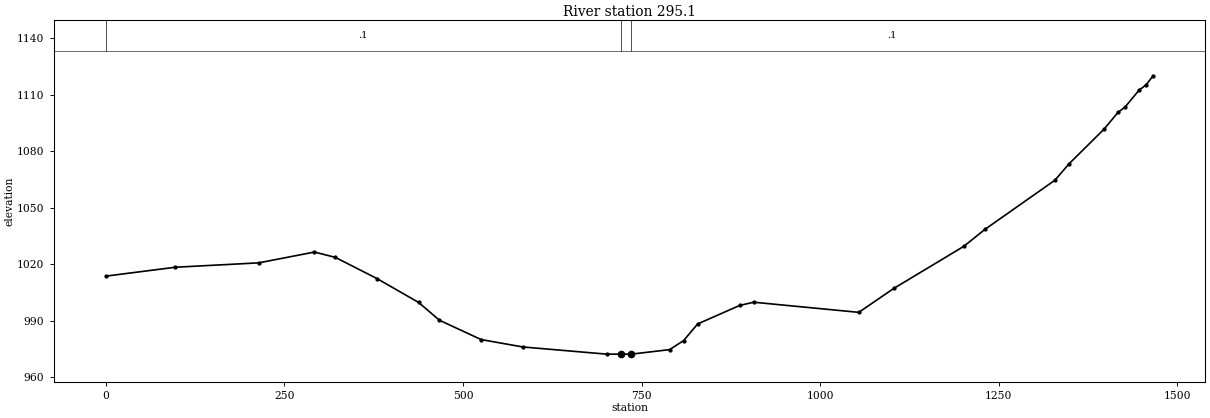
Type RM Length L Ch R = 1 ,295.1,291.266,295.08,298.894
XS GIS Cut Line= 3
     1722594.315      374032.832     1723236.037      374010.808
     1724050.849      373888.291
#Sta/Elev= 30
       0 1013.66    97.3 1018.38   214.0 1020.71   291.9 1026.45   321.1 1023.64
   379.4 1012.39   437.8  999.68   467.0  990.21   525.4  979.93   583.7  976.01
   701.0  972.20   720.7  972.20   735.7  972.20   789.2  974.59   808.9  979.41
   828.5  988.24   887.3  998.07   906.9  999.79  1054.1  994.40  1103.1 1007.12
  1201.2 1029.50  1230.7 1038.50  1328.7 1064.63  1348.4 1073.32  1397.4 1091.73
  1417.0 1100.66  1426.8 1103.48  1446.5 1112.50  1456.3 1115.26  1466.1 1120.11
#Mann= 3 , 0 , 0
       0     0.1       0   720.7   0.045       0   735.7     0.1       0
Bank Sta=   720.7,   735.7
Exp/Cntr=0.3,0.1